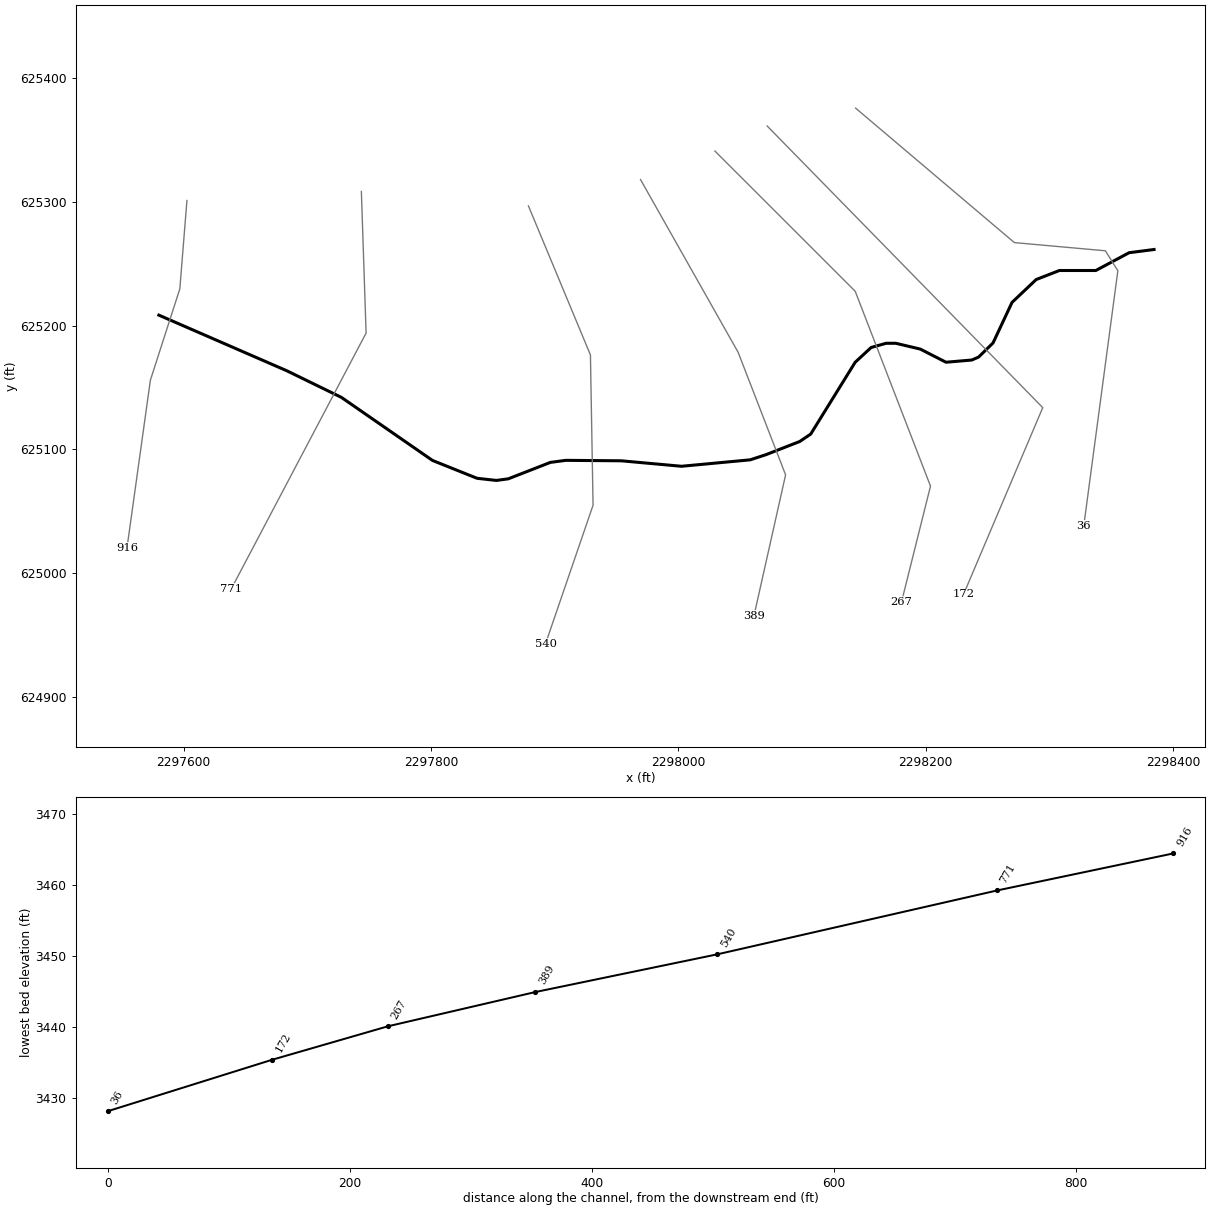
--- MCGEERN2T1.prj (project) ---

Proj Title=MCGEERN2T1
Current Plan=p01
Default Exp/Contr=0,0
English Units
Geom File=g01
Flow File=f01
Plan File=p01
BEGIN DESCRIPTION:
----------MODEL BY WOOD PLC 2022----------
AFH study
Randolph County, WV
HEC-RAS Version: RAS 6.2
Vertical Datum: NAVD88
Projection: NAD 1983 StatePlane West Virginia S FIPS 4702 (US Feet)
Terrain: 1-meter LIDAR (FEMA Region III 3DEP collected 2016-2018)
Land Use: 2019 NLCD
Hydrologic Method:
WV SIR2010-5033 regression equations
Additional Model Notes:
None
END DESCRIPTION:
DSS Export Rating Curves= 0
DSS Export Rating Curve Sorted= 0
DSS Export Volume Flow Curves= 0
DXF OffsetX= 0
DXF OffsetY= 0
DXF ScaleX= 0
DXF ScaleY= 0

--- MCGEERN2T1.p01 (plan) ---

Plan Title=Floodplain
Program Version=6.20
Short Identifier=Floodplain
Geom File=g01
Flow File=f01
Subcritical Flow
K Sum by GR= 0
Std Step Tol= 0.01
Critical Tol= 0.01
Num of Std Step Trials= 20
Max Error Tol= 0.3
Flow Tol Ratio= 0.001
Split Flow NTrial= 30
Split Flow Tol= 0.02
Split Flow Ratio= 0.02
Log Output Level= 0
Friction Slope Method= 1
Unsteady Friction Slope Method= 2
Unsteady Bridges Friction Slope Method= 1
Parabolic Critical Depth
Global Vel Dist= 0 , 0 , 0
Global Log Level= 0
CheckData=True
Encroach Param=-1 ,0,0, 0
Mapping Interval=1HOUR
Computation Time Step Use Courant=        0
Computation Time Step Use Time Series=    0
Computation Time Step Count To Double=0
Computation Time Step Max Doubling=0
Computation Time Step Max Halving=0
Computation Time Step Residence Courant=0
Run HTab= 0
Run UNet= 0
Run Sediment= 0
Run PostProcess= 0
Run WQNet= 0
Run RASMapper=-1
UNET Theta= 0
UNET Theta Warmup= 0
UNET ZTol= 0
UNET ZSATol= 0
UNET MxIter= 0
UNET Max Iter WO Improvement= 0
UNET MaxInSteps= 0
UNET DtIC= 0
UNET DtMin= 0
UNET MaxCRTS= 0
UNET WFStab= 0
UNET SFStab= 0
UNET WFX= 1
UNET SFX= 1
UNET Gravity=32.174
UNET 1D Methodology=Finite Difference
UNET DSS MLevel= 1
UNET Pardiso=0
UNET DZMax Abort= 0
UNET Use Existing IB Tables= 0
UNET Froude Reduction=False
UNET Froude Limit= 0
UNET Froude Power= 0
UNET D1 Cores= 0
UNET WindReference=Eulerian
UNET WindDragFormulation=Hsu (1988)
UNET D2 Coriolis=0
UNET D2 Cores= 0
UNET D2 Theta= 1
UNET D2 Theta Warmup= 1
UNET D2 Z Tol= 0.01
UNET D2 Volume Tol= 0.01
UNET D2 Max Iterations= 20
UNET D2 Equation= 0
UNET D2 RampUpFraction=0.1
UNET D2 TimeSlices= 1
UNET D2 Turbulence Formulation=Non-Conservative (original)
UNET D2 Eddy Viscosity=0.3
UNET D2 Transverse Eddy Viscosity=0.1
UNET D2 Smagorinsky Mixing=0
UNET D2 BCVolumeCheck=0
UNET D2 Cores=0
UNET D2 SolverType=PARDISO (Direct)
UNET D2 Minimum Iterations= 2147483647
UNET D2 Maximum Iterations= 2147483647
UNET D2 Restart Number= 10
UNET D2 Relaxation Coeff=1.3
UNET D2 SOR Precondition Iterations= 10
UNET D2 ILUT Maximum Fill= 8
UNET D2 ILUT Tolerance=1E-08
UNET D1D2 MaxIter= 0
UNET D1D2 ZTol=0.01
UNET D1D2 QTol=0.1
UNET D1D2 MinQTol=1
Write IC File= 0
Write IC File at Fixed DateTime=0
Write IC File at Sim End=0
Echo Input=False
Echo Parameters=False
Echo Output=False
Write Detailed= 0
HDF Write Warmup=0
HDF Write Time Slices=0
HDF Flush=0
HDF Compression= 1
HDF Chunk Size= 1
HDF Spatial Parts= 1
HDF Use Max Rows=0
HDF Fixed Rows= 1
Calibration Method= 0
Calibration Iterations= 20
Calibration Max Change=0.05
Calibration Tolerance=0.2
Calibration Maximum=1.5
Calibration Minimum=0.5
Calibration Optimization Method= 1
WQ AD Non Conservative
WQ ULTIMATE=-1
WQ Max Comp Step=1HOUR
WQ Output Interval=15MIN
WQ Output Selected Increments= 0
WQ Output face flow=0
WQ Output face velocity=0
WQ Output face area=0
WQ Output face dispersion=0
WQ Output cell volume=0
WQ Output cell surface area=0
WQ Output cell continuity=0
WQ Output cumulative cell continuity=0
WQ Output face conc=0
WQ Output face dconc_dx=0
WQ Output face courant=0
WQ Output face peclet=0
WQ Output face adv mass=0
WQ Output face disp mass=0
WQ Output cell mass=0
WQ Output cell source sink temp=0
WQ Output nsm pathways=0
WQ Output nsm derived pathways=0
WQ Create Restart=0
WQ Fixed Restart=0
WQ System Summary=0
WQ Write To DSS=0
Sorting and Armoring Iterations= 10
XS Update Threshold= 0.02
Bed Roughness Predictor= 0
Hydraulics Update Threshold= 0.02
Energy Slope Method= 1
Volume Change Method= 1
Sediment Retention Method= 0
Sediment TS Multiplier= 1
Warm Up Method= 0
XS Weighting Method= 0
Number of US Weighted Cross Sections= 1
Number of DS Weighted Cross Sections= 1
Upstream XS Weight=0
Main XS Weight=1
Downstream XS Weight=0
Number of DS XS's Weighted with US Boundary= 1
Upstream Boundary Weight= 1
Weight of XSs Associated with US Boundary= 0
Number of US XS's Weighted with DS Boundary= 1
Downstream Boundary Weight= 0.5
Weight of XSs Associated with DS Boundary= 0.5
Percentile Method= 0
Sediment Output Level= 3
Mass or Volume Output= 0
Output Increment Type= 1
Profile and TS Output Increment= 1
Transport Output Increment 1
XS Output Flag= 0
XS Output Increment= 10
Read HDF5 Sediment Hotstart= 0
Sediment Hotstart Type= 0
Write Gradation File= 0
Read Gradation Hotstart= 0
Write HDF5 File= 1
Write Binary Output= 1
Write DSS Sediment File= 0
DSS Sediment Output Type= 1
SV Curve= 0
Specific Gage Flag= 0
Subcell Erosion Methods= 0
Subcell Deposition Methods= 0
Advection Scheme= 1
Matrix Solver= 0
Implicit Weighting Factor= 1
Maximum Outer Loop Convergence Iterations= 5
Convergence Maximum Absolute= 0.001
Convergence RMSE= 0.0001
Grain Fractions Max Abs Error= 0.001
Max Subgrid Regions= 1
Max Subgrid Length Scale= 3.402823E+38
Initial Layer Thickness= 3.402823E+38
Min Layer Thickness= 3.402823E+38
Max Layer Thickness= 3.402823E+38
Number of Layers= 5

--- MCGEERN2T1.f01 (steady flow) ---

Flow Title=Flow
Program Version=6.20
Number of Profiles= 1
Profile Names=P100yr
River Rch & RM=MCGEERN2T1,Main,916
     307
Boundary for River Rch & Prof#=MCGEERN2T1,Main            , 1
Up Type= 0
Dn Type= 3
Dn Slope=0.05813
DSS Import GetInterval= 0
DSS Import GetPeak= 0
DSS Import FillOption= 0

--- MCGEERN2T1.g01 (geometry) ---

Geom Title=Geometry
Program Version=6.20

River Reach=MCGEERN2T1      ,Main
Reach XY= 30
2297580.01259224625208.577061121  2297683.423724625163.591511174
2297727.59622916 625142.04394768     2297801.292      625091.015
     2297837.225      625076.616     2297852.855      625074.869
      2297862.49      625076.171     2297896.582      625089.467
     2297909.049      625091.126     2297953.896      625090.754
     2298002.594      625086.327     2298058.063      625091.535
     2298070.823      625095.702     2298098.167      625106.379
     2298107.021      625112.369     2298142.959      625170.442
     2298155.865      625182.395     2298167.976      625185.806
     2298175.771      625185.806     2298195.563      625181.119
      2298216.42      625170.474      2298237.23      625172.264
     2298242.698      625174.608     2298254.417      625186.067
     2298269.782      625218.879     2298289.313      625237.369
     2298308.063       625244.66      2298337.49       625244.66
     2298364.422      625259.048     2298384.604      625261.653

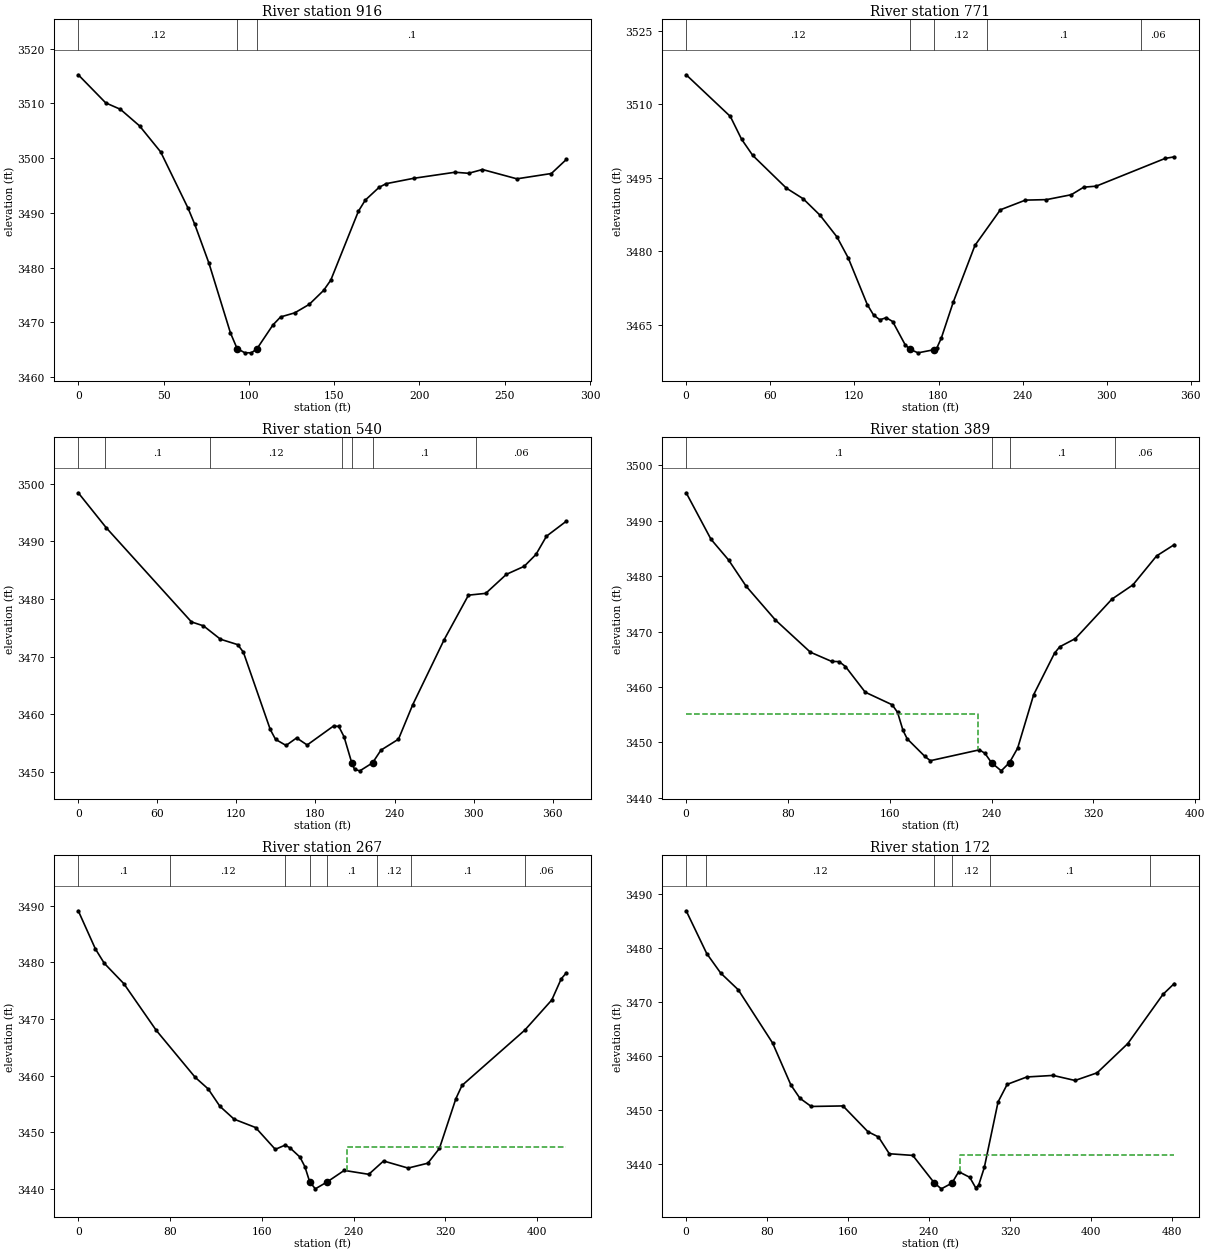
Type RM Length L Ch R = 1 ,916     ,147,145.7,144.5
XS GIS Cut Line= 4
2297602.72069287625301.2739063662297596.97336226625229.842797389
 2297573.1629926625155.9485467232297554.27890632625020.475753836
#Sta/Elev= 30
       0 3515.21    16.1 3510.08    24.7 3508.91    35.9 3505.89    48.3 3501.13
    64.3  3490.9    68.3  3487.9    76.6 3480.82    89.2  3468.1    93.13465.238
    97.6 3464.48   101.4 3464.46   104.6 3465.14   114.1 3469.55   118.6 3471.01
   126.9 3471.76   135.4 3473.31   143.8 3475.85     148 3477.72   164.2  3490.3
   168.2 3492.32   176.3 3494.66   180.4 3495.33   196.5 3496.31   220.8 3497.42
   228.8 3497.23   236.9 3497.92   257.1 3496.22   277.3 3497.19   286.1 3499.76
#Mann= 3 ,0,0
       0     .12       0    93.1    .045       0   104.6      .1       0
Bank Sta=93.1,104.6
XS Rating Curve= 0 ,0
Exp/Cntr(USF)=0,0
Exp/Cntr=0.3,0.1

Type RM Length L Ch R = 1 ,771     ,226.3,231.1,234.5
XS GIS Cut Line= 3
 2297743.7404891625308.6173863462297747.56335553625194.073196724
2297638.70564082624987.434106646
#Sta/Elev= 30
       0    3516    31.5 3507.49    39.5 3502.85    47.5 3499.53    71.5 3492.85
    83.5 3490.68    95.5 3487.32   107.5 3482.92   115.6 3478.61   129.2 3469.08
   133.7 3466.94   138.2 3465.97   142.7 3466.41   147.3 3465.62   156.3 3460.83
  159.973459.912   165.4 3459.23     177 3459.88   178.9 3460.28     182 3462.24
   190.5 3469.57     206 3481.17   224.1 3488.43     242 3490.41     257 3490.51
   274.7 3491.51   283.6 3493.05   292.5 3493.26   341.7 3498.93   348.2 3499.24
#Mann= 5 ,-1,0
       0     .12       0  159.97    .045       0     177     .12       0
  214.61      .1       0  324.61     .06       0
Bank Sta=159.97,177
XS Rating Curve= 0 ,0
Exp/Cntr(USF)=0,0
Exp/Cntr=0.3,0.1

Type RM Length L Ch R = 1 ,540     ,148.3,150.5,153.3
XS GIS Cut Line= 4
2297878.81743823625296.8736594792297928.92538691625176.401357337
2297931.05764005625054.8629286272297892.67708361624942.919639026
#Sta/Elev= 30
       0 3498.43    21.3 3492.35    85.9 3476.04      95 3475.36   107.9 3473.04
     121  3472.1   125.3 3470.79   145.7 3457.39   149.7 3455.68   157.7 3454.62
   165.7 3455.93   173.7  3454.7   193.7 3457.99   197.7 3457.92   201.7 3456.12
   207.6 3451.56   209.7 3450.46   213.7 3450.22   223.3  3451.6   229.7 3453.81
     243 3455.71   253.8 3461.68   277.7 3472.98   296.1 3480.68   309.2 3480.99
   324.9 3484.29   338.4 3485.68   347.3 3487.73   355.3  3490.9   370.4 3493.51
#Mann= 7 ,-1,0
       0     .12       0      20      .1       0     100     .12       0
  200.48      .1       0   207.6    .045       0   223.3      .1       0
  302.03     .06       0
Bank Sta=207.6,223.3
XS Rating Curve= 0 ,0
Exp/Cntr(USF)=0,0
Exp/Cntr=0.3,0.1

Type RM Length L Ch R = 1 ,389     ,121.2,121.7,120.3
XS GIS Cut Line= 4
2297969.43819648625318.1961908322298048.33156248625178.533610472
2298086.71211892625079.383839683 2298061.1250813624965.308296946
#Sta/Elev= 30
       0 3495.02    19.5 3486.64    33.3 3482.91    47.1 3478.18    70.1 3472.09
    97.6 3466.28   114.3 3464.62   120.2 3464.58   125.2 3463.69   140.7 3459.07
   161.9  3456.8   166.1 3455.44   170.4 3452.18   173.7 3450.66   187.6 3447.49
   191.9 3446.72   230.5 3448.68   234.8 3448.04     240 3446.35   247.6 3444.89
   254.1 3446.38   260.5 3448.99   273.1 3458.63   289.5 3466.11   293.6 3467.26
   305.9 3468.74   334.6 3475.85   351.1 3478.42   369.7 3483.64   383.6 3485.67
#Mann= 4 ,-1,0
       0      .1       0     240    .045       0   254.1      .1       0
  336.72     .06       0
#XS Ineff= 2 , 0
          229.03  3455.1
Permanent Ineff=
       F       F
Bank Sta=240,254.1
XS Rating Curve= 0 ,0
Exp/Cntr(USF)=0,0
Exp/Cntr=0.3,0.1

Type RM Length L Ch R = 1 ,267     ,90.6,95.6,98.6
XS GIS Cut Line= 4
2298029.59747002625341.2618250112298142.99243029625227.866864737
2298203.85884279625070.2812214142298180.51282156624976.897136482
#Sta/Elev= 30
       0 3489.08      15 3482.33    22.7 3479.82    39.7 3476.24      68    3468
   101.9 3459.73   113.3 3457.67   123.5 3454.61   135.9 3452.34   154.6 3450.87
   171.8 3447.02   180.4 3447.77   184.7 3447.27   193.3 3445.66   197.6 3443.97
   201.8 3441.29   206.7 3440.06  217.113441.288   231.9 3443.31   253.3 3442.62
   266.2 3444.97   287.6 3443.72   304.8 3444.58   314.9 3447.18   329.3 3455.98
   334.6 3458.29   389.3 3468.03   412.9 3473.36   421.1 3477.08   425.6 3478.15
#Mann= 8 ,-1,0
       0      .1       0      80     .12       0  180.36      .1       0
   201.8    .045       0  217.11      .1       0  260.36     .12       0
  290.36      .1       0   389.3     .06       0
#XS Ineff= 2 , 0
                          234.66          3447.5
Permanent Ineff=
       F       F
Bank Sta=201.8,217.11
XS Rating Curve= 0 ,0
Exp/Cntr(USF)=0,0
Exp/Cntr=0.3,0.1

Type RM Length L Ch R = 1 ,172     ,137.1,136,133.6
XS GIS Cut Line= 3
 2298071.7999236625361.5629122132298294.60679961625133.756294632
2298230.66763515624982.926354621
#Sta/Elev= 30
       0 3486.92    20.3 3478.99    34.1 3475.37    51.5 3472.26    85.4  3462.4
   103.5 3454.61   112.4 3452.15   123.6 3450.62     155 3450.72   179.6 3445.95
   190.1 3444.96   200.8 3441.85     224 3441.54  245.223436.446   252.2 3435.34
  262.723436.404   269.4 3438.52   280.3 3437.48   286.2 3435.53   289.1 3436.02
   294.7  3439.3   308.3 3451.46   317.3 3454.72   336.7 3456.09   362.7 3456.38
   384.4 3455.44   406.2 3456.86   436.6  3462.3   471.3 3471.41   482.5 3473.43
#Mann= 6 ,-1,0
       0      .1       0      20     .12       0  245.22    .045       0
  262.72     .12       0     300      .1       0  458.65     .06       0
#XS Ineff= 2 , 0
                          270.76         3441.59
Permanent Ineff=
       F       F
Bank Sta=245.22,262.72
XS Rating Curve= 0 ,0
Exp/Cntr(USF)=0,0
Exp/Cntr=0.3,0.1

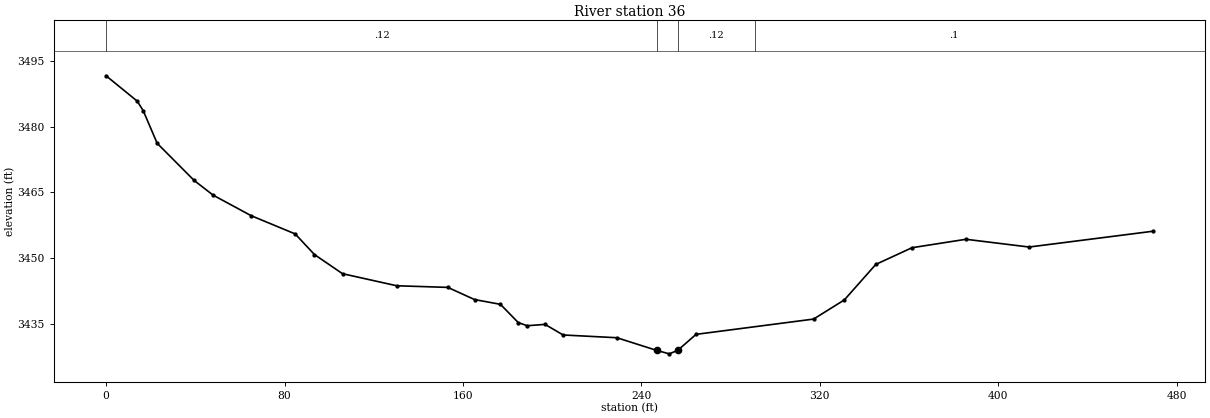
Type RM Length L Ch R = 1 ,36      ,,,
XS GIS Cut Line= 5
2298143.32428998625375.9941083062298271.67002125625267.236124986
2298345.25040616625260.6183402192298355.33040706 625244.49959355
2298327.76418618625038.031986367
#Sta/Elev= 30
       0 3491.59      14 3485.78    16.7 3483.56    22.9 3476.17    39.5 3467.67
      48 3464.32      65 3459.64    84.8 3455.46    93.4 3450.76     106 3446.38
   130.3 3443.62   153.2 3443.25   165.2 3440.47   176.8 3439.38   184.8 3435.21
   188.8 3434.49   196.8  3434.8   204.9 3432.38     229 3431.75  246.91 3428.85
   252.5 3428.07   256.3 3428.87   264.5 3432.52   317.2 3436.01     331 3440.39
   345.1  3448.5   361.3 3452.31   385.5 3454.24   413.8 3452.47   469.4 3456.08
#Mann= 4 ,-1,0
       0     .12       0  246.91    .045       0   256.3     .12       0
  290.97      .1       0
Bank Sta=246.91,256.3
XS Rating Curve= 0 ,0
Exp/Cntr(USF)=0,0
Exp/Cntr=0.3,0.1
LCMann Table=0

Chan Stop Cuts=-1
Use User Specified Reach Order=0
Composite Channel Slope=5